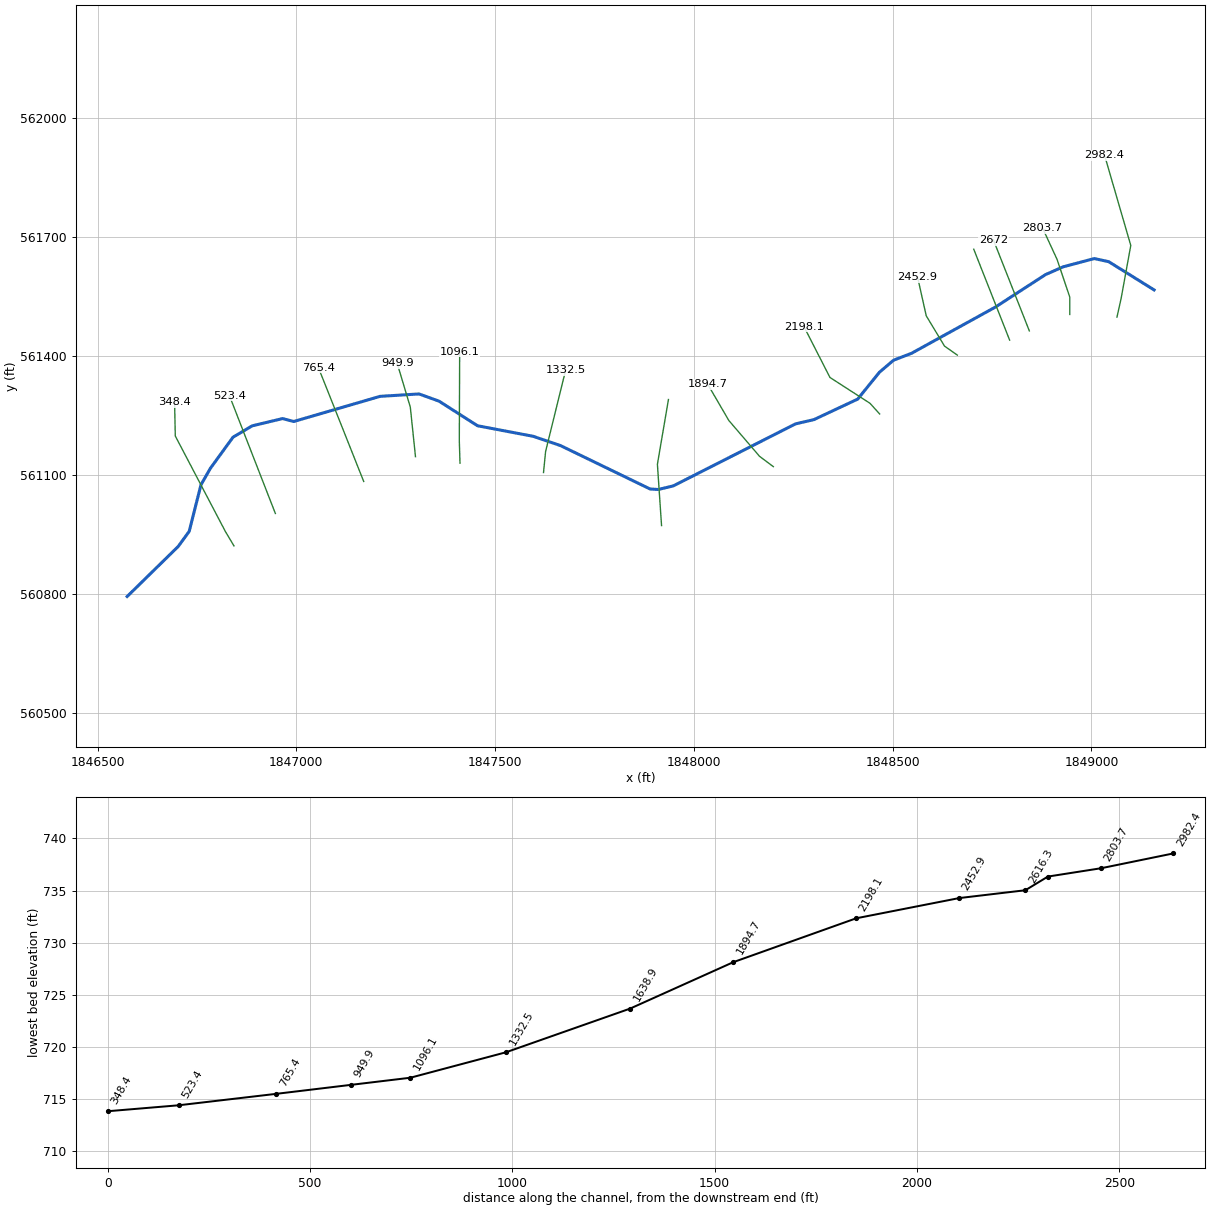
--- HURRICANBR.prj (project) ---

Proj Title=HURRICANBR
Current Plan=p01
Default Exp/Contr=0,0
English Units
Geom File=g01
Flow File=f01
Plan File=p01
BEGIN DESCRIPTION:
END DESCRIPTION:
DSS Export Rating Curves= 0
DSS Export Rating Curve Sorted= 0
DSS Export Volume Flow Curves= 0
DXF OffsetX= 0
DXF OffsetY= 0
DXF ScaleX= 0
DXF ScaleY= 0

--- HURRICANBR.p01 (plan) ---

Plan Title=Floodplain
Program Version=4.00
Geom File=g01
Flow File=f01
K Sum by GR=0
Std Step Tol=0.01
Critical Tol=0.01
Num of Std Step Trials=20
Max Error Tol=0.3
Flow Tol Ratio=0.001
Split Flow NTrial=30
Split Flow Tol=0.02
Split Flow Ratio=0.02
Log Output Level=0
Friction Slope Method=1
Unsteady Friction Slope Method=2
Unsteady Bridges Friction Slope Method=1
Global Log Level=0
CheckData=False
Run HTab=0
Run UNet=0
Run PostProcess=0
UNET Theta=0
UNET Theta Warmup=0
UNET ZTol=0
UNET ZSATol=0
UNET MxIter=0
UNET MaxInSteps=0
UNET DtIC=0
UNET DtMin=0
UNET MaxCRTS=0
UNET WFStab=0
UNET SFStab=0
UNET WFX=0
UNET SFX=0
UNET DSS MLevel=0
UNET DZMax Abort=0
UNET Convert EG Bridges=0
UNET Use Existing IB Tables=0
UNET Froude Limit=0
UNET Froude Power=0
Write IC File=0
Echo Input=False
Echo Output=False
Write Detailed=0

--- HURRICANBR.f01 (steady flow) ---

Flow Title=NFF Regression Equation
Program Version=4.10
Number of Profiles= 1
Profile Names=P100yr
River Rch & RM=HURRICANBR,Main            ,2982.4
986.8971
River Rch & RM=HURRICANBR,Main            ,1332.5
1022.304
River Rch & RM=HURRICANBR,Main            ,523.4
1035.199
Boundary for River Rch & Prof#=HURRICANBR,Main            , 1
Up Type= 0
Dn Type= 3
Dn Slope=0.003
DSS Import GetInterval= 0
DSS Import GetPeak= 0
DSS Import FillOption= 0

--- HURRICANBR.g01 (geometry) ---

Geom Title=USGS 10m DEM
Program Version=4.10

River Reach=HURRICANBR      ,Main
Reach XY= 30
     1849157.548      561566.857     1849043.436      561638.031
     1849006.977      561645.844     1848928.852      561625.011
     1848884.582      561605.479     1848758.279      561523.448
     1848547.468      561407.059     1848502.329      561389.698
     1848466.739      561359.316     1848412.051      561291.608
     1848301.934      561239.891     1848255.675      561229.177
     1847948.384      561072.927     1847910.623      561063.813
      1847889.79      561065.115     1847664.529       561174.49
     1847595.519      561197.927     1847455.892      561224.418
       1847359.1      561286.399     1847308.753      561304.628
     1847210.663      561298.552     1846993.649      561235.184
     1846965.454      561242.539     1846889.187      561224.285
     1846840.916      561195.707     1846783.826      561117.113
     1846760.142      561075.462     1846730.628      560958.274
      1846702.85       560920.08     1846574.502      560794.108

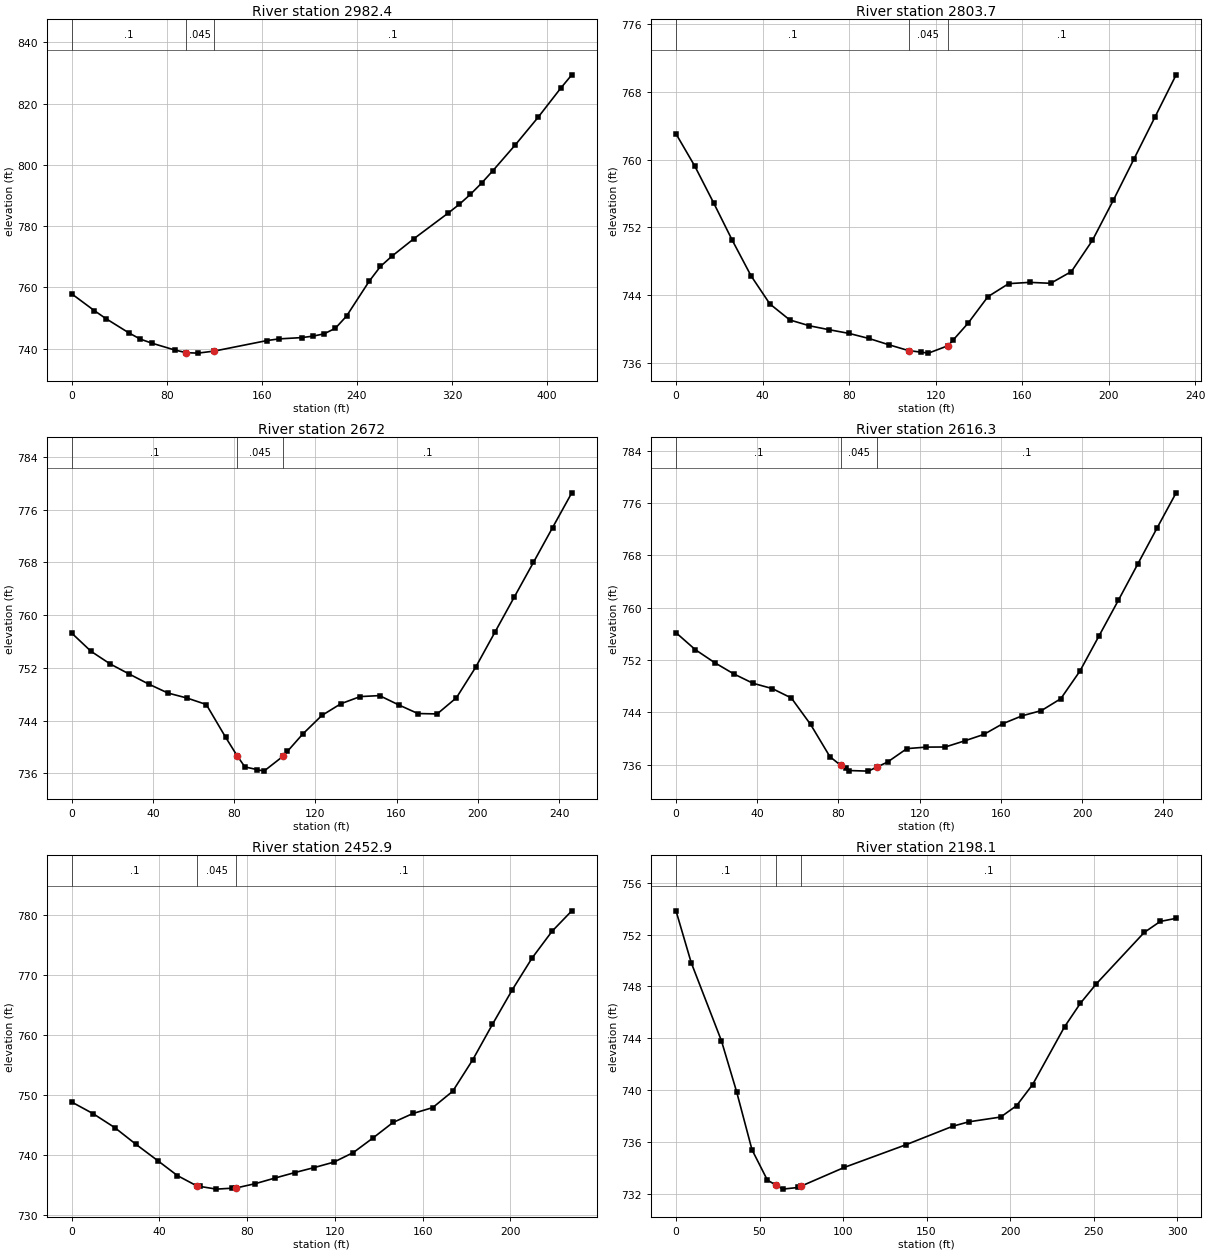
Type RM Length L Ch R = 1 ,2982.4  ,167.1,178.7,190
XS GIS Cut Line= 4
      1849064.25       561498.35     1849074.667      561545.225
     1849098.973      561678.905        1849033.      561906.336
#Sta/Elev= 30
       0  757.93    19.2   752.4    28.8  749.84      48   745.2    57.7  743.14
    67.4  741.82    86.8  739.57    96.5   738.7   106.2  738.56     120  739.23
   164.5  742.68   174.2   743.2   193.4  743.63   202.8  744.09   212.3  744.86
   221.8  746.67   231.2  750.65   250.2     762   259.7  766.85   269.1  770.13
   288.1  775.99   316.5  784.23     326  787.13   335.4   790.4   344.9  794.11
   354.4  798.17   373.3  806.62   392.3  815.54   411.2  824.99   420.7  829.44
#Mann= 3 , 0 , 0
       0      .1       0    96.5    .045       0     120      .1       0
Bank Sta=96.5,120
XS Rating Curve= 0 ,0
Exp/Cntr=0.3,0.1

Type RM Length L Ch R = 1 ,2803.7  ,130.5,131.6,132.7
XS GIS Cut Line= 4
     1848945.616      561505.005     1848945.616      561548.407
     1848913.498      561643.894      1848877.04      561722.887
#Sta/Elev= 28
       0  763.05     8.7  759.23    17.4  754.89      26  750.48    34.7  746.27
    43.4  742.95    52.6  741.06    61.7  740.37    70.9   739.9      80  739.47
    89.2  738.87    98.4  738.13   107.5  737.44   113.1  737.26   116.7  737.14
   125.8  738.02   128.1  738.68     135  740.67   144.2  743.81   153.8  745.35
   163.5   745.5   173.2  745.39   182.8  746.78   192.5  750.46   202.2  755.22
   211.8  760.12   221.5  765.07   231.2  770.02
#Mann= 3 , 0 , 0
       0      .1       0   107.5    .045       0   125.8      .1       0
Bank Sta=107.5,125.8
XS Rating Curve= 0 ,0
Exp/Cntr=0.3,0.1

Type RM Length L Ch R = 1 ,2672    ,55.7,55.7,55.7
XS GIS Cut Line= 2
     1848843.764      561463.627     1848753.487      561692.794
#Sta/Elev= 30
       0  757.27     9.5  754.51      19  752.58    28.4  751.05    37.9  749.54
    47.4  748.18    56.8  747.42    66.3  746.44    75.8  741.48   81.49  738.67
    85.3  736.98    91.2  736.58    94.7  736.34   104.2  738.62   106.2  739.32
   113.7  741.93   123.2  744.78   132.6  746.56   142.1  747.64   151.6  747.79
     161  746.39   170.5  745.07     180  745.01   189.5  747.47   198.9  752.06
   208.4  757.38   217.9  762.69   227.4  767.98   236.8  773.24   246.3  778.53
#Mann= 3 , 0 , 0
       0      .1       0   81.49    .045       0   104.2      .1       0
Bank Sta=81.49,104.2
XS Rating Curve= 0 ,0
Exp/Cntr=0.3,0.1

Type RM Length L Ch R = 1 ,2616.3  ,159.6,163.4,167.3
XS GIS Cut Line= 2
     1848794.285       561440.19     1848704.007      561669.356
#Sta/Elev= 30
       0  756.19     9.5   753.6      19  751.62    28.4   749.9    37.9  748.46
    47.4  747.65    56.8  746.21    66.3  742.16    75.8  737.24   81.05  735.93
    83.8  735.45    85.3  735.12    94.7  735.03    98.8  735.63   104.2  736.42
   113.7  738.47   123.2   738.7   132.6  738.72   142.1  739.65   151.6  740.64
     161  742.29   170.5  743.49     180  744.29   189.5   746.1   198.9  750.31
   208.4  755.74   217.9  761.17   227.4  766.68   236.8  772.13   246.3  777.57
#Mann= 3 , 0 , 0
       0      .1       0   81.05    .045       0    98.8      .1       0
Bank Sta=81.05,98.8
XS Rating Curve= 0 ,0
Exp/Cntr=0.3,0.1

Type RM Length L Ch R = 1 ,2452.9  ,244.4,254.8,265
XS GIS Cut Line= 4
      1848662.63      561402.574     1848630.512      561425.144
     1848584.505      561501.532     1848562.804      561598.755
#Sta/Elev= 28
       0  748.81     9.8  746.86    19.6  744.55    29.4  741.73    39.2  739.04
    48.2  736.54    57.1  734.81    58.3  734.74      66  734.28    73.3  734.44
    74.9  734.47    83.8   735.2    92.8  736.14   101.7  737.04   110.6  737.88
   119.5  738.78   128.4  740.38   137.5  742.85   146.5   745.4   155.6   746.9
   164.6  747.88   173.7   750.6   182.8  755.83   191.8  761.75   200.9  767.55
   209.9  772.83     219  777.29     228   780.7
#Mann= 3 , 0 , 0
       0      .1       0    57.1    .045       0    74.9      .1       0
Bank Sta=57.1,74.9
XS Rating Curve= 0 ,0
Exp/Cntr=0.3,0.1

Type RM Length L Ch R = 1 ,2198.1  ,309.6,303.4,296.5
XS GIS Cut Line= 4
     1848467.318      561254.137     1848443.012      561281.046
     1848342.318       561346.15     1848277.213      561473.755
#Sta/Elev= 23
       0  753.84     9.1  749.84    27.2   743.8    36.3  739.86    45.5  735.38
    54.7  733.04    59.7  732.66    63.9  732.34    73.2  732.47    74.7  732.56
   100.8  734.02   137.7  735.77   165.7   737.2   175.3  737.54   194.4  737.91
   203.9  738.79   213.5  740.42   232.6  744.88   242.1   746.7   251.7  748.21
   280.3  752.17   289.9  753.02   299.4  753.26
#Mann= 3 , 0 , 0
       0      .1       0    59.7    .045       0    74.7      .1       0
Bank Sta=59.7,74.7
XS Rating Curve= 0 ,0
Exp/Cntr=0.3,0.1

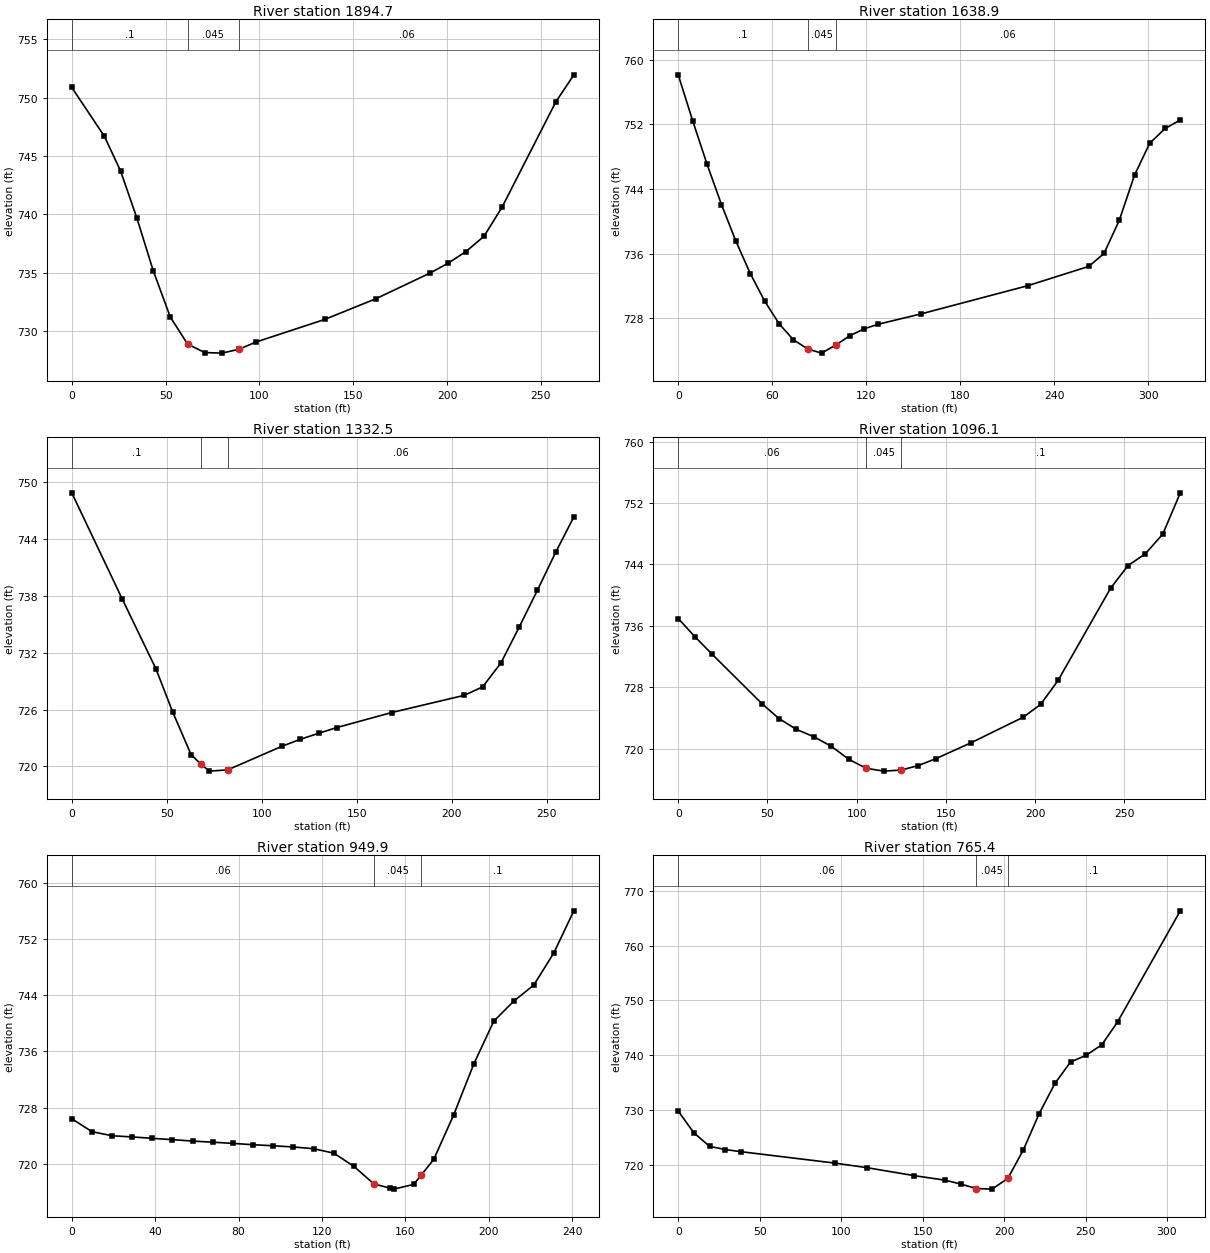
Type RM Length L Ch R = 1 ,1894.7  ,270.5,255.7,241.3
XS GIS Cut Line= 4
     1848199.957      561121.324     1848165.234      561147.366
     1848087.977      561237.644     1848035.026      561328.789
#Sta/Elev= 20
       0  750.86    17.4  746.68      26  743.72    34.7  739.69    43.4   735.2
    52.5  731.23    61.7  728.92    70.8  728.19      80  728.14    89.1  728.47
    98.2  729.09   134.8  731.02   162.2   732.8     191  734.99   200.6  735.83
   210.1  736.83   219.7  738.13   229.3  740.61     258  749.63   267.6  751.94
#Mann= 3 , 0 , 0
       0      .1       0    61.7    .045       0    89.1     .06       0
Bank Sta=61.7,89.1
XS Rating Curve= 0 ,0
Exp/Cntr=0.3,0.1

Type RM Length L Ch R = 1 ,1638.9  ,313.4,306.4,299.4
XS GIS Cut Line= 4
     1847918.707      560972.887     1847914.366      561037.123
      1847908.29        561127.4     1847936.068      561290.595
#Sta/Elev= 24
       0  758.11     9.2  752.44    18.4  747.04    27.6  742.06    36.8  737.53
      46  733.52    55.2   730.1    64.4  727.31    73.4  725.35    82.5   724.2
    91.5  723.68   100.6  724.69   109.6  725.84   118.7  726.69   127.7  727.26
   154.9  728.53     223  732.02     262  734.41   271.7  736.01   281.5  740.14
   291.2  745.71   300.9  749.65   310.7  751.47   320.4  752.53
#Mann= 3 , 0 , 0
       0      .1       0    82.5    .045       0   100.6     .06       0
Bank Sta=82.5,100.6
XS Rating Curve= 0 ,0
Exp/Cntr=0.3,0.1

Type RM Length L Ch R = 1 ,1332.5  ,229.7,236.4,243.1
XS GIS Cut Line= 3
     1847621.832      561106.567      1847627.04      561159.519
     1847677.387       561364.38
#Sta/Elev= 20
       0  748.86    26.6  737.64    44.3  730.29    53.2  725.69    62.8  721.24
   68.02  720.22    72.4   719.5      82  719.63   110.7  722.13   120.3  722.86
   129.9  723.49   139.5   724.1   168.3  725.68   206.6   727.5   216.2  728.39
   225.8   730.9   235.4  734.68     245  738.57   254.6  742.57   264.2  746.32
#Mann= 3 , 0 , 0
       0      .1       0   68.02    .045       0      82     .06       0
Bank Sta=68.02,82
XS Rating Curve= 0 ,0
Exp/Cntr=0.3,0.1

Type RM Length L Ch R = 1 ,1096.1  ,140.4,146.2,151
XS GIS Cut Line= 3
     1847411.762      561130.005     1847410.026      561186.428
     1847410.894      561411.255
#Sta/Elev= 23
       0  736.95     9.4  734.57    18.8  732.34      47  725.83    56.4  723.92
    66.2   722.5      76  721.54    85.8  720.29    95.6   718.6   105.3  717.43
   115.1  717.06   124.9   717.2   134.6  717.79   144.4  718.69     164  720.75
   193.3  724.09   203.1  725.77   212.8  728.88   242.2  740.89     252  743.86
   261.7  745.39   271.5  747.97   281.3  753.34
#Mann= 3 , 0 , 0
       0     .06       0   105.3    .045       0   124.9      .1       0
Bank Sta=105.3,124.9
XS Rating Curve= 0 ,0
Exp/Cntr=0.3,0.1

Type RM Length L Ch R = 1 ,949.9   ,182.9,184.5,186.7
XS GIS Cut Line= 3
     1847299.783      561146.498     1847286.762      561271.498
     1847253.776      561381.741
#Sta/Elev= 28
       0   726.4     9.7  724.56    19.3  723.98      29  723.81    38.7  723.61
    48.3  723.42      58  723.22    67.7  723.06    77.3  722.89      87   722.7
    96.7  722.55   106.3  722.38     116  722.13   125.7   721.5   135.3  719.62
   144.9  717.12   152.5  716.53   154.4  716.38     164  717.05   167.5  718.35
   173.6  720.61   183.2  726.97   192.8  734.19   202.4  740.29     212  743.15
   221.6  745.43   231.2  750.01   240.8     756
#Mann= 3 , 0 , 0
       0     .06       0   144.9    .045       0   167.5      .1       0
Bank Sta=144.9,167.5
XS Rating Curve= 0 ,0
Exp/Cntr=0.3,0.1

Type RM Length L Ch R = 1 ,765.4   ,242.2,242,241.8
XS GIS Cut Line= 2
     1847169.575      561083.998     1847055.859      561370.456
#Sta/Elev= 21
       0  729.78     9.6   725.8    19.3  723.33    28.9  722.75    38.5  722.36
    96.3  720.27   115.6  719.45   144.5     718   163.7  717.16   173.4  716.45
     183  715.63   192.6  715.52   202.3  717.47   211.9  722.72   221.5  729.27
   231.2  734.82   240.8  738.74   250.4  739.97     260  741.89   269.7  746.07
   308.2  766.36
#Mann= 3 , 0 , 0
       0     .06       0     183    .045       0   202.3      .1       0
Bank Sta=183,202.3
XS Rating Curve= 0 ,0
Exp/Cntr=0.3,0.1

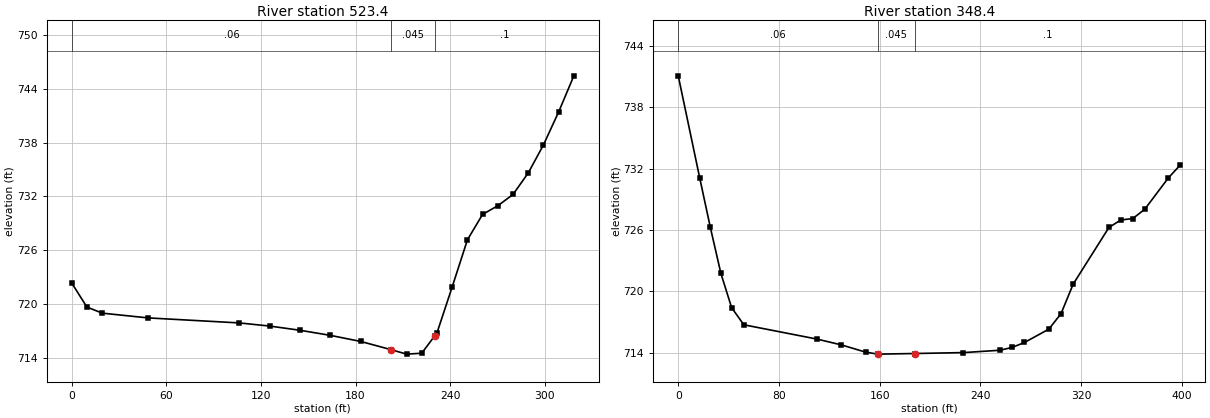
Type RM Length L Ch R = 1 ,523.4   ,178.6,175,176
XS GIS Cut Line= 2
     1846947.352      561003.269     1846831.901      561300.144
#Sta/Elev= 23
       0  722.34     9.6  719.67    19.3  718.99    48.3  718.46   106.2   717.9
   125.5  717.55   144.8  717.08   164.1  716.51   183.4  715.83   202.7  714.91
   212.4  714.42     222  714.52   230.3  716.47   231.7   716.8   241.3   721.9
     251  727.17   260.6     730   270.3  730.97   279.9  732.22   289.6  734.63
   299.2  737.74   308.9  741.44   318.5  745.45
#Mann= 3 , 0 , 0
       0     .06       0   202.7    .045       0   230.3      .1       0
Bank Sta=202.7,230.3
XS Rating Curve= 0 ,0
Exp/Cntr=0.3,0.1

Type RM Length L Ch R = 1 ,348.4   ,335.4,348.4,356.6
XS GIS Cut Line= 4
     1846843.186      560921.671     1846821.484       560958.13
     1846695.616      561198.581      1846693.88       561283.65
#Sta/Elev= 24
       0  741.07      17  731.12    25.5  726.25    33.9  721.74    42.4   718.4
    52.1  716.72   110.3  715.32   129.7  714.75     149  714.04   158.7  713.85
   187.8  713.91   226.6     714   255.7  714.23   265.4  714.51   275.1  714.99
   294.4  716.29   304.1   717.8   313.8   720.7   342.2  726.24   351.6  726.97
   361.1  727.11   370.6  728.01   389.5   731.1   398.9  732.35
#Mann= 3 , 0 , 0
       0     .06       0   158.7    .045       0   187.8      .1       0
Bank Sta=158.7,187.8
XS Rating Curve= 0 ,0
Exp/Cntr=0.3,0.1

Chan Stop Cuts=-1
Use User Specified Reach Order=0
Composite Channel Slope=5